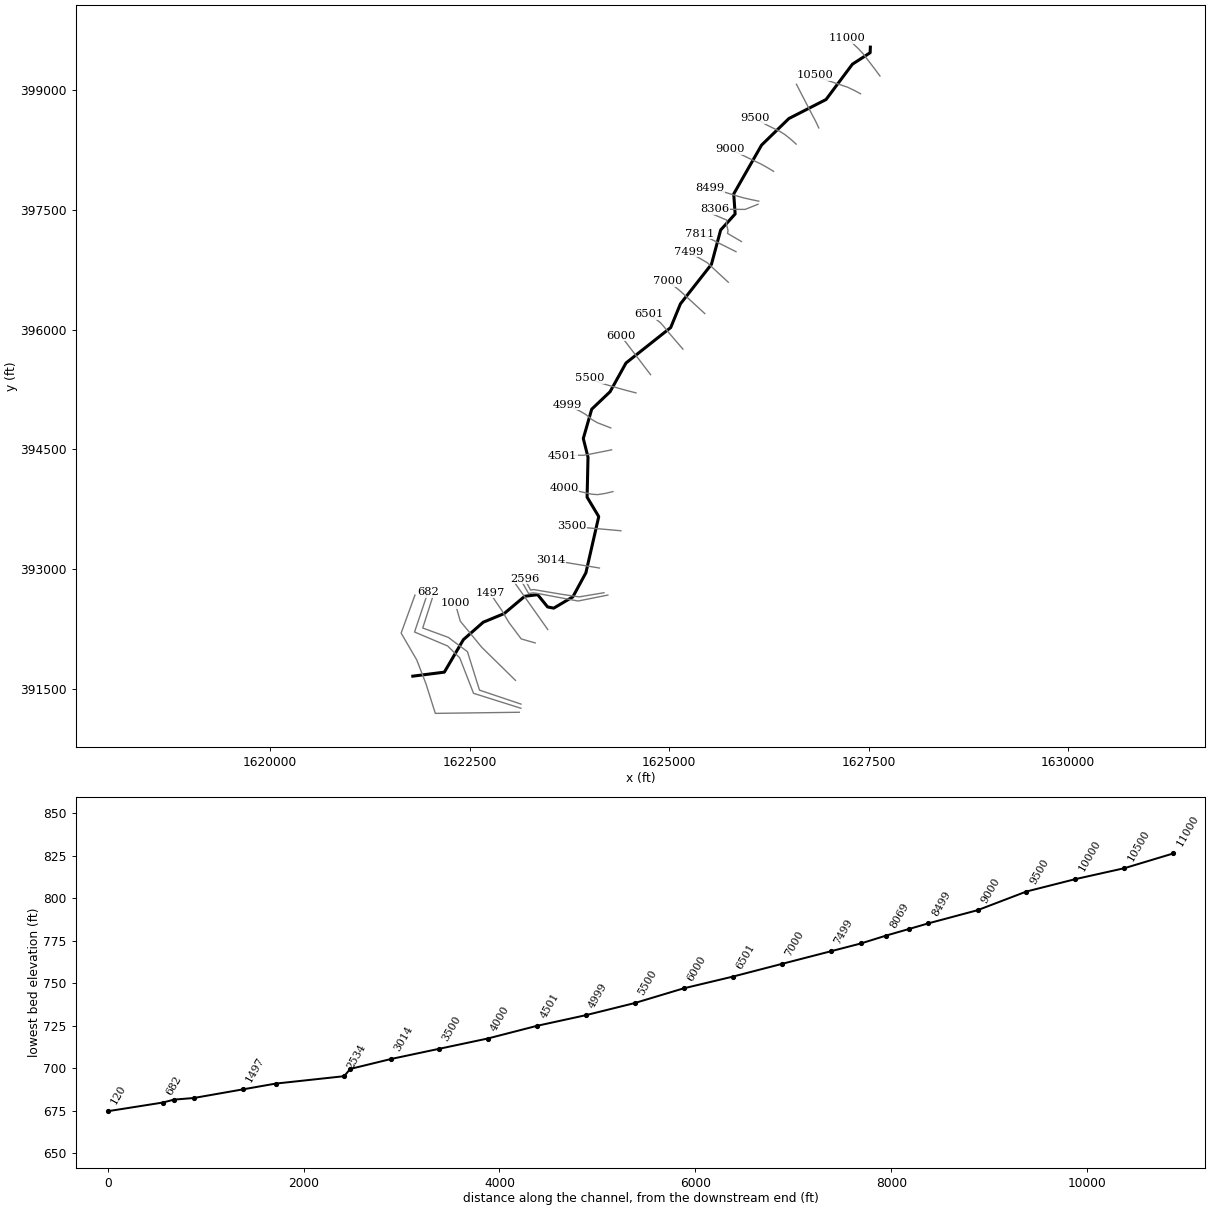
--- READERCK.prj (project) ---

Proj Title=READERCK
Current Plan=p01
Default Exp/Contr=0,0
English Units
Geom File=g01
Flow File=f01
Plan File=p01
BEGIN DESCRIPTION:
---------- MODELED AS PART OF WVEMD CTP PROGRAM, 2023----------
Stream Name: Reader Creek
Flood Zone:  AFH
Wetzel County, WV
HEC-RAS Version: RAS 6.3
Vertical Datum: NAVD88
Projection: NAD 1983 StatePlane West Virginia S FIPS 4702 (US Feet)
Terrain: 1-meter West Virginia FEMA R3 South Central (collected 2018-2020)
Land Use: 2019 NLCD
Hydrologic Method:
WV SIR2010-5033 regression equations
Additional Model Notes:
Leveraged XS
END DESCRIPTION:
DSS Export Rating Curves= 0
DSS Export Rating Curve Sorted= 0
DSS Export Volume Flow Curves= 0
DXF OffsetX= 0
DXF OffsetY= 0
DXF ScaleX= 0
DXF ScaleY= 0

--- READERCK.p01 (plan) ---

Plan Title=Floodplain
Program Version=6.30
Short Identifier=Floodplain
Geom File=g01
Flow File=f01
Subcritical Flow
K Sum by GR= 0
Std Step Tol= 0.01
Critical Tol= 0.01
Num of Std Step Trials= 20
Max Error Tol= 0.3
Flow Tol Ratio= 0.001
Split Flow NTrial= 30
Split Flow Tol= 0.02
Split Flow Ratio= 0.02
Log Output Level= 0
Friction Slope Method= 1
Unsteady Friction Slope Method= 2
Unsteady Bridges Friction Slope Method= 1
Parabolic Critical Depth
Global Vel Dist= 0 , 0 , 0
Global Log Level= 0
CheckData=True
Encroach Param=-1 ,0,0, 0
Mapping Interval=1HOUR
Computation Time Step Use Courant=        0
Computation Time Step Use Time Series=    0
Computation Time Step Count To Double=0
Computation Time Step Max Doubling=0
Computation Time Step Max Halving=0
Computation Time Step Residence Courant=0
Run HTab= 0
Run UNet= 0
Run Sediment= 0
Run PostProcess= 0
Run WQNet= 0
Run RASMapper= 0
UNET Theta= 0
UNET Theta Warmup= 0
UNET ZTol= 0
UNET ZSATol= 0
UNET MxIter= 0
UNET Max Iter WO Improvement= 0
UNET MaxInSteps= 0
UNET DtIC= 0
UNET DtMin= 0
UNET MaxCRTS= 0
UNET WFStab= 0
UNET SFStab= 0
UNET WFX= 1
UNET SFX= 1
UNET Gravity=32.17405
UNET 1D Methodology=Finite Difference
UNET DSS MLevel= 1
UNET Pardiso=0
UNET DZMax Abort= 0
UNET Use Existing IB Tables= 0
UNET Froude Reduction=False
UNET Froude Limit= 0
UNET Froude Power= 0
UNET D1 Cores= 0
UNET WindReference=Eulerian
UNET WindDragFormulation=Hsu (1988)
UNET D2 Coriolis=0
UNET D2 Cores= 0
UNET D2 Theta= 1
UNET D2 Theta Warmup= 1
UNET D2 Z Tol= 0.01
UNET D2 Volume Tol= 0.01
UNET D2 Max Iterations= 20
UNET D2 Equation= 0
UNET D2 RampUpFraction=0.1
UNET D2 TimeSlices= 1
UNET D2 Turbulence Formulation=Non-Conservative (original)
UNET D2 Eddy Viscosity=0.3
UNET D2 Transverse Eddy Viscosity=0.1
UNET D2 Smagorinsky Mixing=0
UNET D2 BCVolumeCheck=0
UNET D2 Cores=0
UNET D2 SolverType=PARDISO (Direct)
UNET D2 Minimum Iterations= 3
UNET D2 Maximum Iterations= 30
UNET D2 Restart Number= 10
UNET D2 Relaxation Coeff=1.3
UNET D2 SOR Precondition Iterations= 10
UNET D2 ILUT Maximum Fill= 8
UNET D2 ILUT Tolerance=1E-08
UNET D2 Convergence Tolerance=0.00001
UNET D1D2 MaxIter= 0
UNET D1D2 ZTol=0.01
UNET D1D2 QTol=0.1
UNET D1D2 MinQTol=1
Write IC File= 0
Write IC File at Fixed DateTime=0
Write IC File at Sim End=0
Echo Input=False
Echo Parameters=False
Echo Output=False
Write Detailed= 0
HDF Write Warmup=0
HDF Write Time Slices=0
HDF Flush=0
HDF Compression= 1
HDF Chunk Size= 1
HDF Spatial Parts= 1
HDF Use Max Rows=0
HDF Fixed Rows= 1
Calibration Method= 0
Calibration Iterations= 20
Calibration Max Change=0.05
Calibration Tolerance=0.2
Calibration Maximum=1.5
Calibration Minimum=0.5
Calibration Optimization Method= 1
WQ AD Non Conservative
WQ ULTIMATE=-1
WQ Max Comp Step=1HOUR
WQ Output Interval=15MIN
WQ Output Selected Increments= 0
WQ Output face flow=0
WQ Output face velocity=0
WQ Output face area=0
WQ Output face dispersion=0
WQ Output cell volume=0
WQ Output cell surface area=0
WQ Output cell continuity=0
WQ Output cumulative cell continuity=0
WQ Output face conc=0
WQ Output face dconc_dx=0
WQ Output face courant=0
WQ Output face peclet=0
WQ Output face adv mass=0
WQ Output face disp mass=0
WQ Output cell mass=0
WQ Output cell source sink temp=0
WQ Output nsm pathways=0
WQ Output nsm derived pathways=0
WQ Create Restart=0
WQ Fixed Restart=0
WQ System Summary=0
WQ Write To DSS=0
Sorting and Armoring Iterations= 10
XS Update Threshold= 0.02
Bed Roughness Predictor= 0
Hydraulics Update Threshold= 0.02
Energy Slope Method= 1
Volume Change Method= 1
Sediment Retention Method= 0
Sediment TS Multiplier= 1
Warm Up Method= 0
XS Weighting Method= 0
Number of US Weighted Cross Sections= 1
Number of DS Weighted Cross Sections= 1
Upstream XS Weight=0
Main XS Weight=1
Downstream XS Weight=0
Number of DS XS's Weighted with US Boundary= 1
Upstream Boundary Weight= 1
Weight of XSs Associated with US Boundary= 0
Number of US XS's Weighted with DS Boundary= 1
Downstream Boundary Weight= 0.5
Weight of XSs Associated with DS Boundary= 0.5
Percentile Method= 0
Sediment Output Level= 3
Mass or Volume Output= 0
Output Increment Type= 1
Profile and TS Output Increment= 1
Transport Output Increment 1
XS Output Flag= 0
XS Output Increment= 10
Read HDF5 Sediment Hotstart= 0
Sediment Hotstart Type= 0
Write Gradation File= 0
Read Gradation Hotstart= 0
Write HDF5 File= 1
Write Binary Output= 1
Write DSS Sediment File= 0
DSS Sediment Output Type= 1
SV Curve= 0
Specific Gage Flag= 0
Subcell Erosion Methods= 0
Subcell Deposition Methods= 0
Advection Scheme= 1
Matrix Solver= 0
Implicit Weighting Factor= 1
Maximum Outer Loop Convergence Iterations= 5
Convergence Maximum Absolute= 0.001
Convergence RMSE= 0.0001
Grain Fractions Max Abs Error= 0.001
Max Subgrid Regions= 1
Max Subgrid Length Scale= 3.402823E+38
Initial Layer Thickness= 3.402823E+38
Min Layer Thickness= 3.402823E+38
Max Layer Thickness= 3.402823E+38
Number of Layers= 5

--- READERCK.f01 (steady flow) ---

Flow Title=Flow
Program Version=4.00
Number of Profiles=1
Profile Names=F01pct
River Rch & RM=READERCK,Main,11000
     595
River Rch & RM=READERCK,Main,9500
     767
River Rch & RM=READERCK,Main,8306
     874
River Rch & RM=READERCK,Main,4999
    1010
River Rch & RM=READERCK,Main,2596
    1180
Boundary for River Rch & Prof#=READERCK,Main      ,1
Up Type=0
Dn Type=3
Dn Slope=0.00706

--- READERCK.g01 (geometry) ---

Geom Title=Geometry
Program Version=6.31

River Reach=READERCK        ,Main
Reach XY= 30
     1627522.046      399541.383     1627519.189      399471.031
     1627297.344      399327.554     1626966.986      398884.465
     1626500.989      398645.739     1626159.009      398313.043
     1625810.228      397700.748     1625827.976       397449.58
     1625646.641      397248.568     1625530.895      396817.608
     1625142.761      396322.988     1625020.842      396025.522
     1624461.019      395581.444     1624261.165      395221.089
     1624030.831      395001.558     1623925.647      394633.824
     1623984.725      394399.921     1623973.271       393898.96
     1624119.159      393655.411       1623958.2      392950.689
      1623794.83      392649.267     1623555.502        392507.6
     1623478.338      392522.671     1623353.858       392676.32
     1623192.264       392656.41     1622933.898      392439.253
     1622671.829      392330.906     1622423.187      392112.361
     1622184.703      391704.961     1621789.673      391654.846

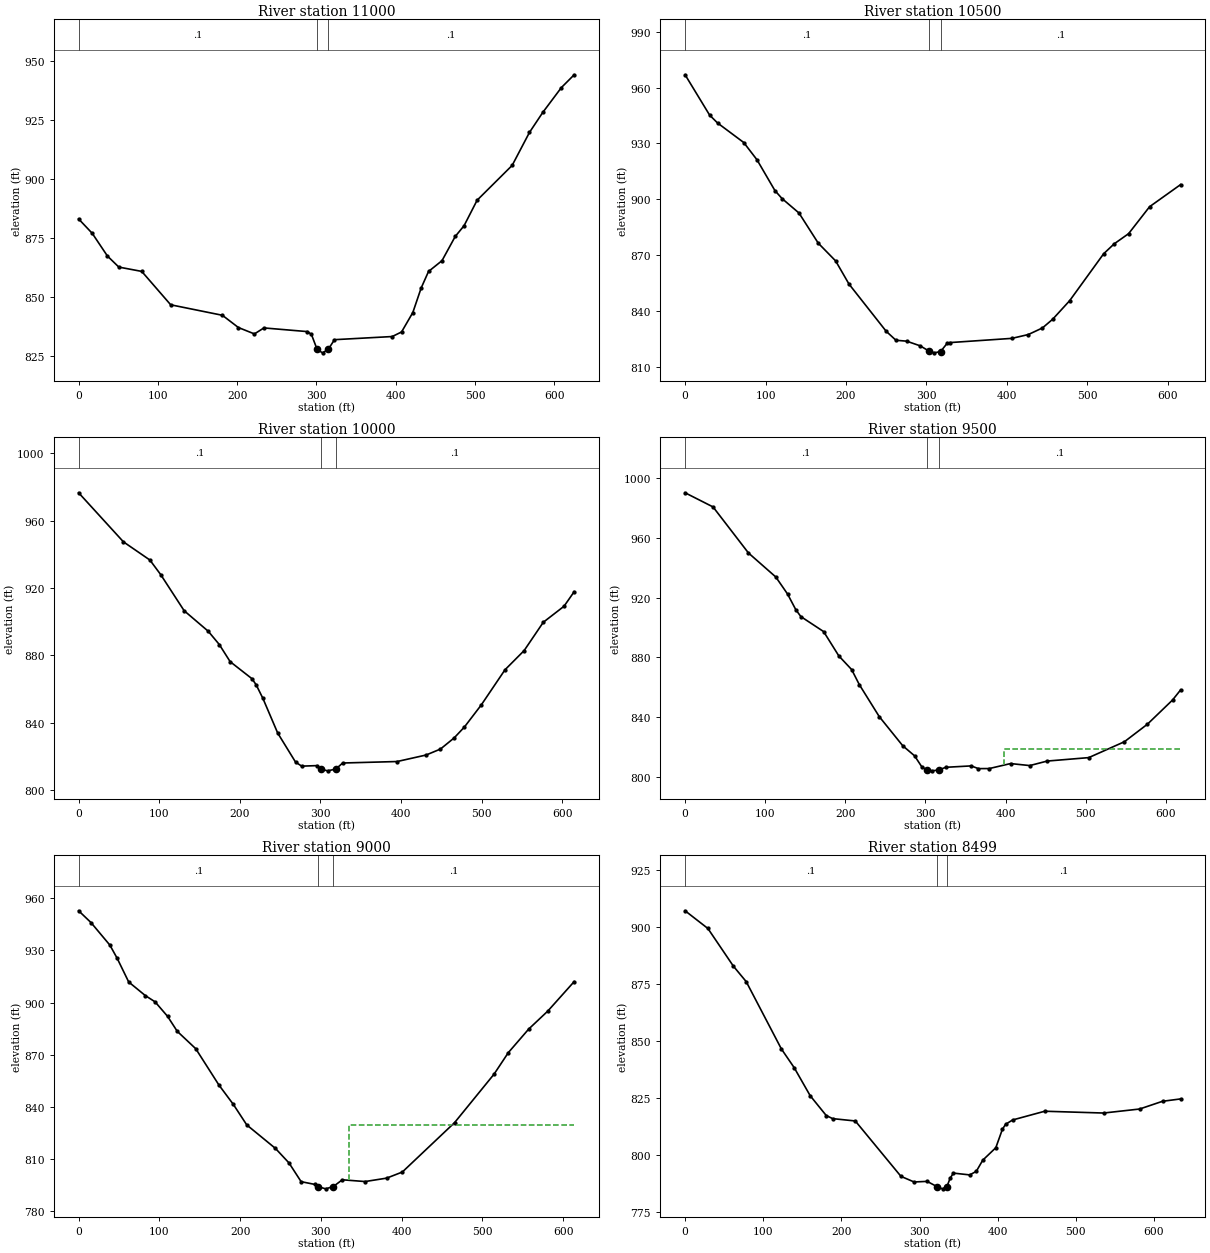
Type RM Length L Ch R = 1 ,11000   ,496.2,499.8,504.3
XS GIS Cut Line= 6
1627642.36006884399179.4384877531627586.42284475399254.689977676
1627533.64276659399324.4834732561627426.80242909 399463.08424592
1627375.26611485399518.6038199221627235.45865168399651.580260009
#Sta/Elev= 30
       0  883.19    17.2  877.08    36.3  867.49    50.7  862.79    79.6  860.96
   116.1  846.81   181.3  842.36   201.5  837.17   221.7  834.46   233.7     837
   288.6  835.44   293.6  834.27  300.77827.8978   307.6  826.44   314.8  827.91
   322.7  832.02   395.5  833.35   407.3  835.29   421.5  843.53     432  853.91
   441.3  860.93   458.3  865.51     475  875.78   486.1  880.31   502.6  891.14
   546.8   905.9   568.6  919.87   585.4  928.35   608.9   938.9     625  944.31
#Mann= 3 ,-1,0
       0      .1       0  300.77    .045       0   314.8      .1       0
Bank Sta=300.77,314.8
XS Rating Curve= 0 ,0
Exp/Cntr(USF)=0,0
Exp/Cntr=0.3,0.1

Type RM Length L Ch R = 1 ,10500   ,504.4,500.2,493
XS GIS Cut Line= 6
1627399.00163168 398956.705337421627314.56183992399001.834840342
1627234.54592384399039.8829925951627068.60235809399095.457684591
1626914.80739009 399147.990716011626828.96077701399187.165506423
#Sta/Elev= 30
       0  966.83    30.5  945.21    40.4  940.97    72.9  930.52    89.4  921.25
   111.7  904.75   120.6  900.44   141.6  892.73   165.6  876.54   187.2  867.03
   203.8  854.62     250  829.33   262.2  824.49   275.5  824.01   292.3  821.51
   303.7  818.59     310  817.75   317.7  818.46   325.8  822.82     329  823.24
   406.4  825.51   426.8  827.56   444.4  831.11   457.1  835.77   478.2  845.71
   520.5  870.89   533.6   876.2   551.5  881.65   577.6   896.1   616.2  907.97
#Mann= 3 ,-1,0
       0      .1       0   303.7    .045       0   317.7      .1       0
Bank Sta=303.7,317.7
XS Rating Curve= 0 ,0
Exp/Cntr(USF)=0,0
Exp/Cntr=0.3,0.1

Type RM Length L Ch R = 1 ,10000   ,494.9,500.5,505.2
XS GIS Cut Line= 6
1626875.70379376398528.4581624271626835.11168334398615.174196333
1626793.60061151398692.5208264291626759.20369868398759.168002844
1626713.33764867398848.0293736761626595.80802809399075.736923501
#Sta/Elev= 30
       0   976.5    55.6  947.34    88.4  936.55   101.8   927.9   130.9  906.44
   160.8  894.24   174.5  886.36     188  876.16   215.1  866.03   220.3  862.38
   228.6  854.37     247  833.73   269.1  816.52   276.7   814.1   296.1  814.42
   300.4  812.38   308.9  811.31  319.02812.3671   327.6  815.96   395.1  816.84
   431.1  820.71   448.9  824.25   465.9  830.87   478.6  837.33   499.4  850.36
     529  871.36   552.7  882.74   576.5  899.58   602.2  909.08   614.8  917.73
#Mann= 3 ,-1,0
       0      .1       0   300.4    .045       0  319.02      .1       0
Bank Sta=300.4,319.02
XS Rating Curve= 0 ,0
Exp/Cntr(USF)=0,0
Exp/Cntr=0.3,0.1

Type RM Length L Ch R = 1 ,9500    ,497.6,499.5,498.4
XS GIS Cut Line= 6
1626592.49602684398325.2400649191626521.95286085398388.635279343
1626452.83423267 398443.927491591626389.20640717398484.376885757
1626230.31860159398562.1191843451626071.36550742 398652.32733725
#Sta/Elev= 30
       0  990.28    34.9  980.79    79.1  949.94   113.2  933.87   127.9  922.44
   138.2  911.93   144.5  907.34   172.9  897.29   191.9  880.98   207.9  871.83
   217.4   861.8   242.3  840.35   271.7  820.78   286.4  814.07   295.8  806.39
   301.8  804.66   308.5     804   316.9  804.63   325.3  806.37   357.1  807.31
     366  805.49   379.6  805.53   406.2  808.87   430.2  807.53   451.9  810.55
   503.8  812.86   548.3  823.49   577.1  835.27   608.4  851.45   618.5  858.24
#Mann= 3 ,-1,0
       0      .1       0   301.8    .045       0   316.9      .1       0
#XS Ineff= 2 , 0
                          398.57          818.48
Permanent Ineff=
       F       F
Bank Sta=301.8,316.9
XS Rating Curve= 0 ,0
Exp/Cntr(USF)=0,0
Exp/Cntr=0.3,0.1

Type RM Length L Ch R = 1 ,9000    ,500,500.8,501.5
XS GIS Cut Line= 6
1626309.23773509397984.2263112521626228.27890751398033.002132341
1626151.49526842398075.5637270061626083.88155851398108.019698843
1625993.72950783398151.2929062551625762.71487801398262.181792095
#Sta/Elev= 30
       0  952.71    15.3  945.94    38.7  932.98    47.7  925.43      62  911.81
    82.6  903.99    94.7  900.39   110.1  892.09   122.1  883.48     145  873.49
   173.7  852.63   191.6  841.47   208.2   829.7   243.7  816.21   260.5  807.86
   275.5  797.11   292.5  795.53     297  794.18   305.9  792.99   315.4  794.33
   326.5  798.19   354.7  797.18   381.3  799.13   400.8  802.64   465.6  831.07
   514.4  858.87   532.1  871.25   557.3  884.77   580.9  895.08   613.6  912.03
#Mann= 3 ,-1,0
       0      .1       0     297    .045       0   315.4      .1       0
#XS Ineff= 2 , 0
                          335.15          829.66
Permanent Ineff=
       F       F
Bank Sta=297,315.4
XS Rating Curve= 0 ,0
Exp/Cntr(USF)=0,0
Exp/Cntr=0.3,0.1

Type RM Length L Ch R = 1 ,8499    ,193.6,193.7,193.7
XS GIS Cut Line= 6
1626124.66067642397610.027256504 1626024.6139605397630.775902674
1625930.54525101397652.0370150061625854.59067851397674.435920343
1625603.47766368397750.9433132561625514.04674017 397779.12140651
#Sta/Elev= 30
       0   907.2    29.2  899.43    61.8  882.91    78.2  876.13   123.2  846.62
   139.6   838.4   160.1  826.09   180.6  817.42   188.8  816.06   217.8  815.03
   276.2  790.75     293  788.28   309.7  788.54  322.94786.1321   329.4  785.27
   334.9  786.14   339.1  789.88   343.3  792.17   364.2  791.38   372.6  792.93
   380.9  797.84   397.6   803.3     406  811.36   410.1  813.57   419.1  815.47
   460.2   819.3   535.5  818.51   581.6  820.27   610.9  823.66   634.1   824.7
#Mann= 3 ,-1,0
       0      .1       0  322.94    .045       0   334.9      .1       0
Bank Sta=322.94,334.9
XS Rating Curve= 0 ,0
Exp/Cntr(USF)=0,0
Exp/Cntr=0.3,0.1

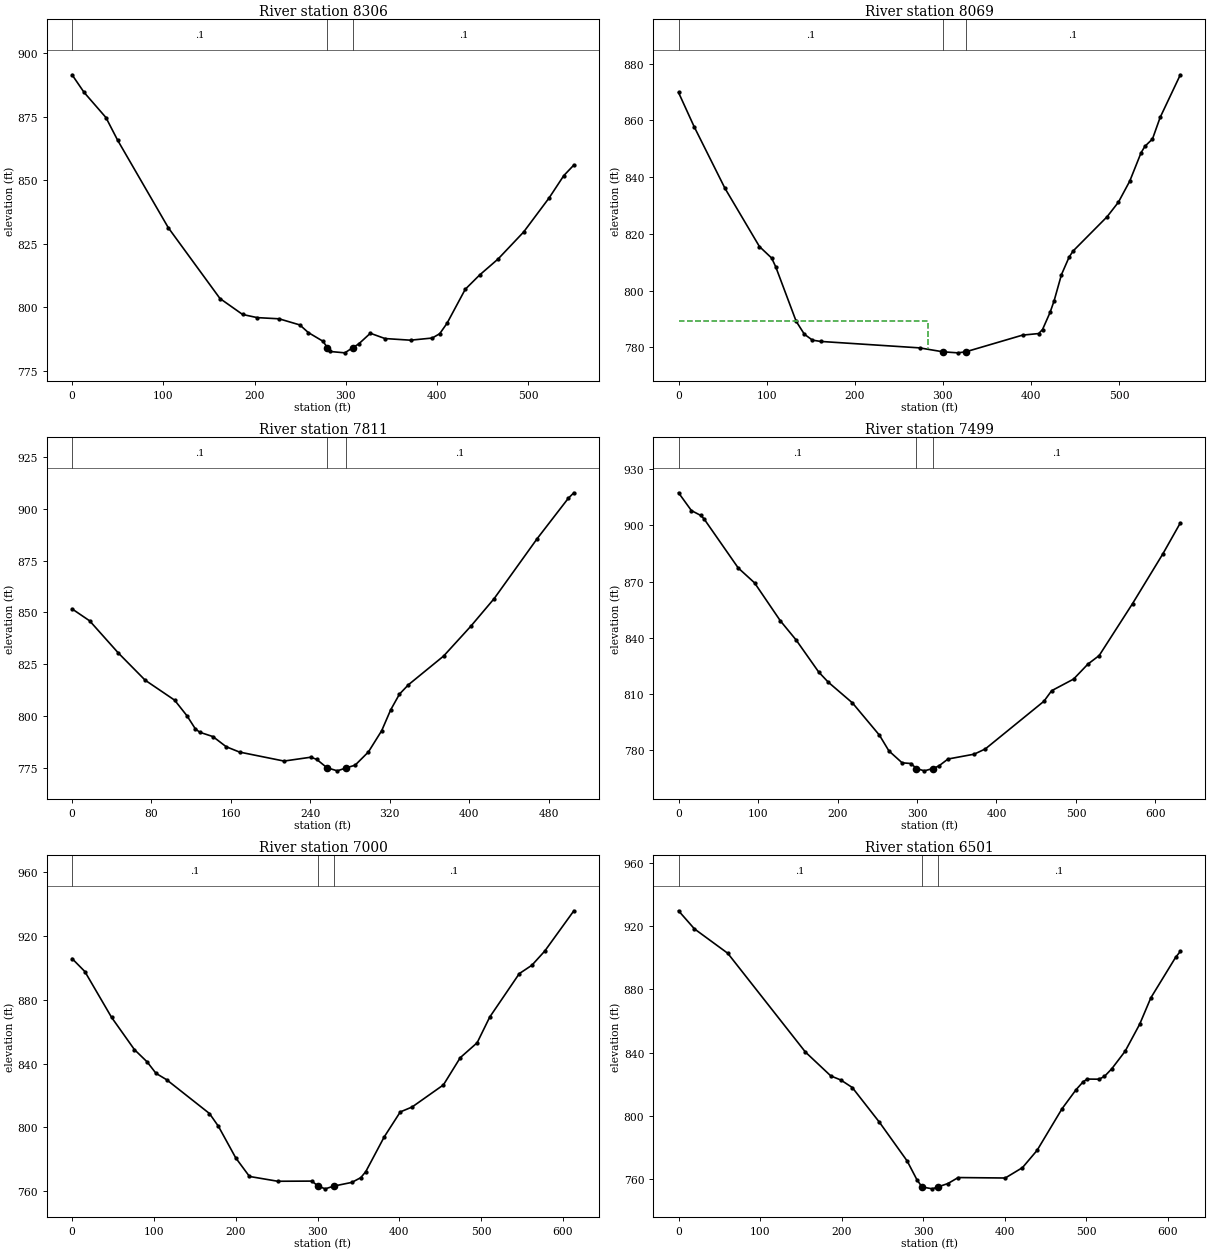
Type RM Length L Ch R = 1 ,8306    ,250.8,236.2,216.7
XS GIS Cut Line= 3
 1626114.5806071397571.2588571821625953.24292019397506.723782421
 1625577.0956273397509.489571339
#Sta/Elev= 30
       0  891.51    13.2  884.56    37.1  874.68      50   865.7   105.5  831.26
   162.1   803.4   186.9  797.12   202.9  795.88   226.9  795.41   249.6     793
   258.9     790   274.9  786.59   279.9  784.04   282.9  782.54   298.9  782.01
   307.7  784.05   314.1  785.51   326.9  789.72   342.9  787.64   370.9  786.99
   394.7  787.84   402.9  789.54   410.9  793.64   430.9  807.04   446.7  812.68
   466.9  818.97   494.9   829.6   522.9  843.07   538.9  851.81549.9235  855.97
#Mann= 3 ,-1,0
       0      .1       0   279.9    .045       0   307.7      .1       0
Bank Sta=279.9,307.7
XS Rating Curve= 0 ,0
Exp/Cntr(USF)=0,0
Exp/Cntr=0.3,0.1

Type RM Length L Ch R = 1 ,8069    ,250.1,257.9,270.6
BEGIN DESCRIPTION:
Low water crossing
END DESCRIPTION:
XS GIS Cut Line= 6
1625907.33970022397103.6163319461625731.97980672397206.174719959
1625739.35524384397239.3641869791625719.07279177397325.103643448
1625722.76051033  397373.04398471625542.81591867397449.354436339
#Sta/Elev= 30
       0  869.83    17.7  857.79    52.7  836.06    91.8  815.55   105.7  811.48
   110.3  808.41   133.5  789.21   142.8  784.65     152  782.56   161.3  782.11
   273.5  779.84   300.2  778.45   316.8  778.09  325.83  778.44   390.5  784.34
   408.7  784.88   413.1   786.3   421.7  792.36   426.2  796.38   434.6  805.65
   443.2  811.77   447.7  813.94   486.3  826.02   499.2  831.16   512.1   838.6
     525  848.64   529.3  850.86   537.9  853.45   546.6  861.05   569.5  876.07
#Mann= 3 ,-1,0
       0      .1       0   300.2    .045       0  325.83      .1       0
#XS Ineff= 2 , 0
          283.48  789.31
Permanent Ineff=
       F       F
Bank Sta=300.2,325.83
XS Rating Curve= 0 ,0
Exp/Cntr(USF)=0,0
Exp/Cntr=0.3,0.1

Type RM Length L Ch R = 1 ,7811    ,313.8,312.3,307.2
XS GIS Cut Line= 2
 1625838.9236449396976.6142397351625387.17812157 397203.40893104
#Sta/Elev= 30
       0  851.63    17.7  845.87    46.7  830.29    73.6  817.22   103.3  807.57
   115.7  800.06     124  793.85   128.5  792.09   141.9  789.98   155.3  785.07
   168.7   782.5   213.5  778.16   240.5  780.02   246.4  778.98  256.77  774.94
   267.2  773.44   276.2  774.87   276.2  774.88   285.1  776.16   298.5  782.55
   311.9  792.83   320.9  802.84   329.8  810.48   338.8  814.99   374.3  828.88
   401.5  843.17   425.2  856.61   468.6  885.61     500  905.11505.4798   907.7
#Mann= 3 ,-1,0
       0      .1       0  256.77    .045       0   276.2      .1       0
Bank Sta=256.77,276.2
XS Rating Curve= 0 ,0
Exp/Cntr(USF)=0,0
Exp/Cntr=0.3,0.1

Type RM Length L Ch R = 1 ,7499    ,498.8,499.2,498.9
XS GIS Cut Line= 6
1625742.28906584396593.5220716741625554.32028167396767.600791752
1625481.70789409396836.3755885961625413.32679726396877.197357342
1625330.69966592396924.0437203351625243.57812101   396974.030497
#Sta/Elev= 30
       0  917.47    16.2  907.95      28  905.34      32  903.57    75.1  877.26
    95.6  869.32   128.1  848.99     148  838.71   176.3  821.63   188.3  816.21
   218.8  805.09   252.8   787.8   264.7   779.4   281.3  773.05   292.5  772.68
  299.28769.9894   309.3  768.76   319.8  769.98   327.4  771.34     339  775.08
     372  777.68     386  780.49   459.7  805.97   469.4  811.61     497  817.83
   515.1  825.87   529.2  830.41   571.2  858.21   609.3  884.78   631.3  901.34
#Mann= 3 ,-1,0
       0      .1       0  299.28    .045       0   319.8      .1       0
Bank Sta=299.28,319.8
XS Rating Curve= 0 ,0
Exp/Cntr(USF)=0,0
Exp/Cntr=0.3,0.1

Type RM Length L Ch R = 1 ,7000    ,500.6,499.4,497.7
XS GIS Cut Line= 6
1625447.56360543396200.9031062571625314.28007933396323.732585013
1625185.59300075396442.3271640841625129.57900517396492.217156172
1625061.49744843396547.4716388431624988.23545584396606.760890335
#Sta/Elev= 30
       0  905.88    15.6  897.75    48.2  869.03    76.2  848.73    91.7  841.04
   102.6  833.82   115.4  829.88   167.9  808.61   178.8  800.63   200.1  780.69
   216.8   769.1   251.3  766.09     293  766.19   300.5  763.11   309.3  761.33
   320.2   763.1   341.9  765.38   352.8  768.35   358.9  772.12   381.5  793.97
   401.1  809.62   415.5  812.69   453.8  826.58   474.4  843.68     495  853.02
   510.4  869.17   546.5  896.43   561.9  901.69   577.6  910.57   613.2  935.88
#Mann= 3 ,-1,0
       0      .1       0   300.5    .045       0   320.2      .1       0
Bank Sta=300.5,320.2
XS Rating Curve= 0 ,0
Exp/Cntr(USF)=0,0
Exp/Cntr=0.3,0.1

Type RM Length L Ch R = 1 ,6501    ,500.9,500.7,500.2
XS GIS Cut Line= 6
  1625173.987709395754.8731584251625006.90897493395949.407546252
1624943.66664734396026.8808165041624894.65755901396083.687461421
1624825.54910143396139.0948309151624747.31992717396194.061584502
#Sta/Elev= 30
       0  929.74    19.5  918.29    60.4  902.86   155.7  840.37   186.9  825.26
   199.1  822.71   213.2  817.94   246.5  795.98   280.5   771.5   292.5  759.62
   298.8  755.04   311.5  753.86  317.99755.0538   330.4  757.17   343.1     761
   400.9  760.71     422  767.28   439.9  778.17   470.6  804.56   487.9  816.66
   496.5  821.59   501.4  823.29     516  823.21   522.6  824.98   531.6  829.81
     548  840.92   565.8  857.96   579.5  874.66   609.8   900.2   615.7  904.06
#Mann= 3 ,-1,0
       0      .1       0   298.8    .045       0  317.99      .1       0
Bank Sta=298.8,317.99
XS Rating Curve= 0 ,0
Exp/Cntr(USF)=0,0
Exp/Cntr=0.3,0.1

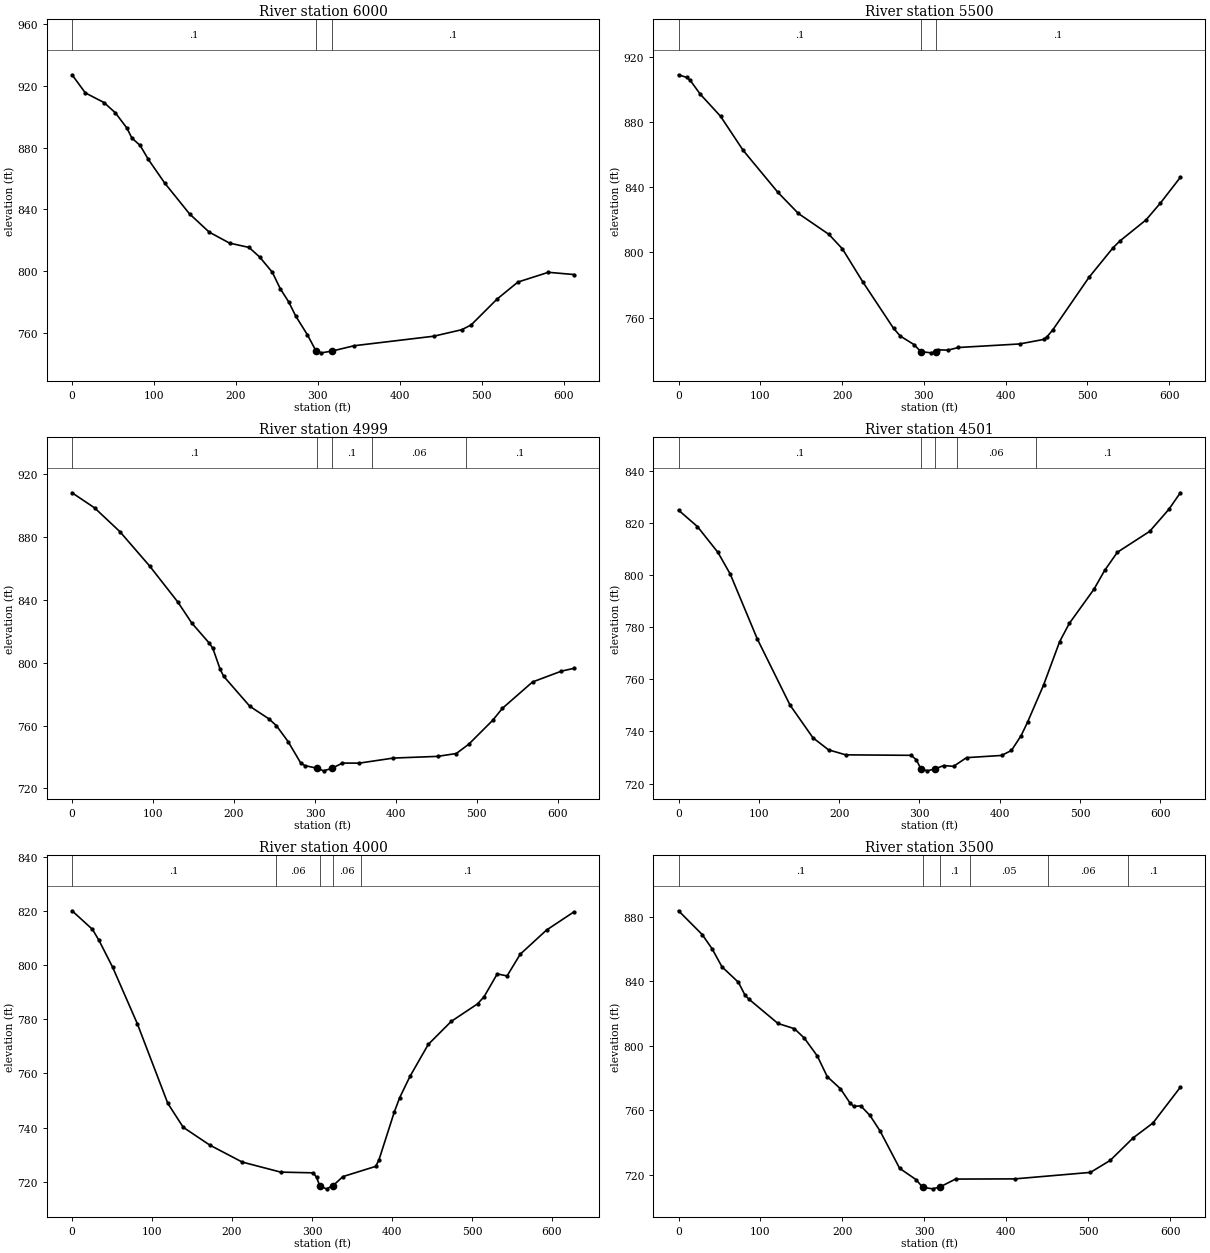
Type RM Length L Ch R = 1 ,6000    ,493.9,500,505.9
XS GIS Cut Line= 6
1624768.73622292395434.4807545841624658.84044534395578.598248512
1624613.33397467395638.2149271671624507.15242851395777.320948169
1624454.09052676395846.9067670111624397.24123101395921.458783254
#Sta/Elev= 30
       0  927.34    16.2  915.59      39  909.33    52.9  902.64      67  892.71
      73   886.3    83.1  881.49    93.1  872.45   113.2  857.01   143.4  837.11
   167.4  825.27   192.3  818.14     216  815.35     229  809.12   244.5   799.2
   254.1  788.59   264.5  779.95     273  770.82   287.3  758.64   297.8  748.16
   304.4  746.97   317.6  748.16   344.4  751.59   441.4  757.75   475.7  761.98
   487.1  765.05   518.7  781.82   544.2  792.88   581.4  799.21   612.5  797.76
#Mann= 3 ,-1,0
       0      .1       0   297.8    .045       0   317.6      .1       0
Bank Sta=297.8,317.6
XS Rating Curve= 0 ,0
Exp/Cntr(USF)=0,0
Exp/Cntr=0.3,0.1

Type RM Length L Ch R = 1 ,5500    ,504,500.5,496.7
XS GIS Cut Line= 6
1624585.89964634395206.0619200921624495.07699335395229.625193179
1624410.53483959395252.2599904241624170.47298376395322.047252417
1624088.01842426395351.8644500081624001.97594543395391.383727923
#Sta/Elev= 30
       0   909.1    10.1  907.47    14.2  905.73    26.6  897.17    51.4   883.6
      79  862.69   121.7  836.79   146.6  823.89   183.9  811.06   200.5  802.12
   225.5  781.77     263  753.33   271.3  748.57     288  743.37   296.3  739.07
   308.8   738.3  314.37  739.05   317.2  740.12   329.7  739.98   342.2  741.58
   417.1  743.75   446.6  746.54   450.8  748.24   457.8  752.47   501.9  784.61
   531.5  802.91   539.8  807.02   571.7  819.93   589.4  830.33   613.7  846.07
#Mann= 3 ,0,0
       0      .1       0   296.3    .045       0  314.37      .1       0
Bank Sta=296.3,314.37
XS Rating Curve= 0 ,0
Exp/Cntr(USF)=0,0
Exp/Cntr=0.3,0.1

Type RM Length L Ch R = 1 ,4999    ,492.2,498.4,506.6
XS GIS Cut Line= 6
1624270.27987076394767.0874043411624098.41833784394833.838255093
 1624033.4447145394872.3673775051623956.06626034394935.721581504
1623890.32164118394973.9567412591623726.38135226395056.910971671
#Sta/Elev= 30
       0  908.31    27.8  898.69      59  883.59      96  861.52   130.6  838.72
   147.9  825.29   169.6  812.42   173.9  809.15   182.6   796.3   187.1  791.48
   219.6  772.24   242.9  764.34   252.3  759.98   266.8  749.81   282.4  736.17
   287.5  734.49     303  732.75   310.7  731.14   320.7  732.69     334  736.08
   354.8  736.06   396.9  739.28   451.4  740.35   474.6  742.18     490  748.11
   519.6  763.37   531.5  770.95   568.8  787.78   604.5  794.67   619.8  796.44
#Mann= 5 ,-1,0
       0      .1       0     303    .045       0   320.7      .1       0
  369.96     .06       0  486.01      .1       0
Bank Sta=303,320.7
XS Rating Curve= 0 ,0
Exp/Cntr(USF)=0,0
Exp/Cntr=0.3,0.1

Type RM Length L Ch R = 1 ,4501    ,503.5,501,496.4
XS GIS Cut Line= 6
1624280.27755417394492.1752245131624029.00345042394441.921716094
1623930.49314876 394424.416501761623851.64947443394424.107447252
1623759.60143018394421.4975443331623662.01140226394415.684563845
#Sta/Elev= 30
       0  825.08    23.6  818.75    49.1  808.84    64.4   800.5    98.1  775.57
   138.9  750.13   167.4  737.59   186.8  732.95   208.2  731.02   289.7  730.83
   296.2  729.12   301.8  725.67     310  724.87  319.79725.6596   330.3   726.9
   342.5  726.59   358.7  729.94   402.4  730.79   414.7  732.72   426.7   738.4
   434.7  743.57   454.7  757.88   474.7  774.54   486.7  781.53   517.5  794.71
   530.7   801.9   546.6   808.9   586.8  816.92   610.7  825.39     625  831.76
#Mann= 5 ,-1,0
       0      .1       0   301.8    .045       0  319.79      .1       0
  346.25     .06       0  445.15      .1       0
Bank Sta=301.8,319.79
XS Rating Curve= 0 ,0
Exp/Cntr(USF)=0,0
Exp/Cntr=0.3,0.1

Type RM Length L Ch R = 1 ,4000    ,496.2,500.1,496.8
XS GIS Cut Line= 6
1624296.88677293 393968.801271261624198.41945018393945.422380999
1624105.84778492393930.7639457581624029.80823883393936.338081583
1623932.34058601393958.701225832 1623682.7922006394016.435362339
#Sta/Elev= 30
       0  820.01    25.5  813.15    33.7  809.06    50.7   799.2    81.6  778.33
   119.7  748.95     139  740.12   172.4  733.53   212.7  727.31   260.8   723.6
   301.6  723.33   305.7  721.63   309.8  718.39   318.1  717.43   326.4  718.65
   338.6  721.95   379.6  725.72   383.7  728.16   402.9  745.84   409.6   751.1
   422.4   758.9   445.3  770.72     474   779.2   506.9  785.67   515.1  788.32
   531.5  796.72   543.8  795.98   560.3     804   593.1  812.89   627.3  819.59
#Mann= 5 ,-1,0
       0      .1       0  254.93     .06       0   309.8    .045       0
   326.4     .06       0  361.17      .1       0
Bank Sta=309.8,326.4
XS Rating Curve= 0 ,0
Exp/Cntr(USF)=0,0
Exp/Cntr=0.3,0.1

Type RM Length L Ch R = 1 ,3500    ,486.5,486,485.4
XS GIS Cut Line= 6
1624396.93578543393477.7737100121624303.54850501393486.014507174
  1624216.387262393493.7051085831624141.67743768393500.297615096
1623967.35462359393515.6788179281623786.80642825393531.611856923
#Sta/Elev= 30
       0  883.61    28.9  868.88      41  860.04      53  848.89    73.1  839.31
    81.1  831.37    85.9  828.84   121.4  813.78   141.4  810.56   153.4   804.8
   169.4  793.63   181.5  780.85   197.6  773.35   209.6   764.3   213.7  762.46
   222.5  762.72   233.7  756.77   245.8  747.35   269.9  724.02   289.9  717.03
     298  712.29     310  711.32   318.7712.3724   338.1  717.37   410.4  717.49
   502.8  721.51   526.9  728.94     555  742.92   579.1  752.12   612.5  774.26
#Mann= 6 ,-1,0
       0      .1       0     298    .045       0   318.7      .1       0
  356.25     .05       0  451.25     .06       0  548.75      .1       0
Bank Sta=298,318.7
XS Rating Curve= 0 ,0
Exp/Cntr(USF)=0,0
Exp/Cntr=0.3,0.1

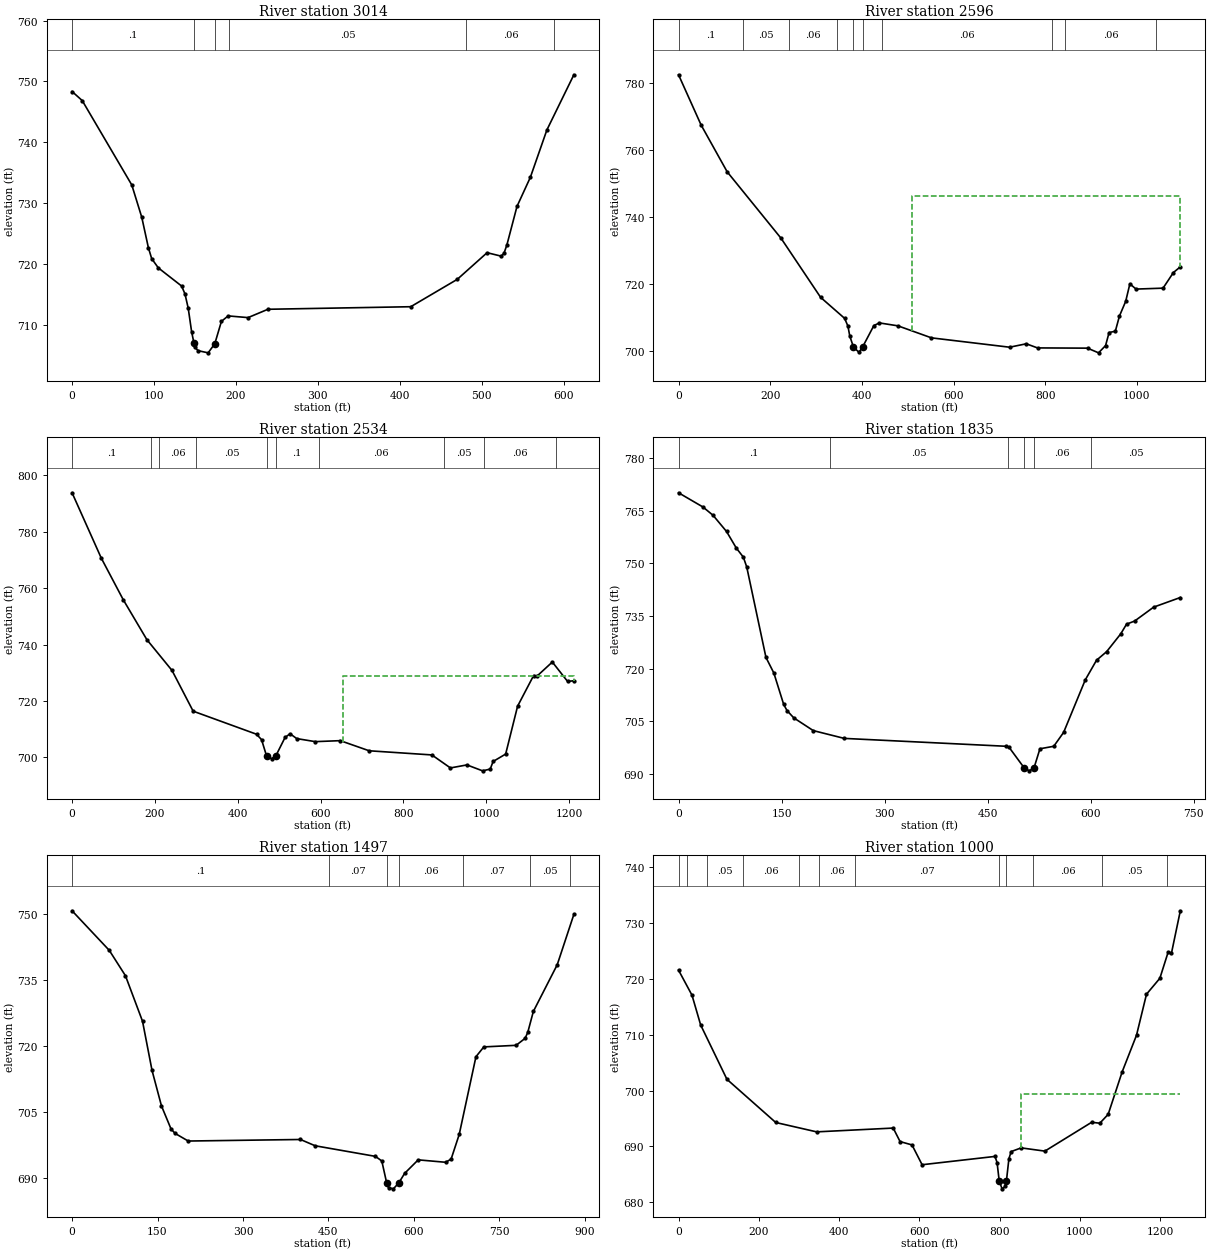
Type RM Length L Ch R = 1 ,3014    ,418.1,417.8,416.8
BEGIN DESCRIPTION:
Structure 2 XS 4
END DESCRIPTION:
XS GIS Cut Line= 6
1624128.02380447393010.5119112061624035.51808396393025.838324122
1623949.17934589393040.0463009551623702.49676838393080.639067538
 1623616.1580303393094.8467162771623523.68511814393110.167551778
#Sta/Elev= 30
       0  748.33    12.4  746.84    72.9  732.97    85.1  727.65    93.2  722.63
    97.2  720.86   105.3  719.34   133.7  716.36   137.8  715.07   141.8   712.7
   145.9  708.87   148.7707.0243   149.9  706.27     154  705.73   166.1  705.38
   174.2  706.87   182.3  710.55   190.5  711.45   214.8  711.17   239.1  712.54
   413.4  712.96   470.2  717.46   506.6  721.84   523.8  721.27   527.2  721.74
   530.7  723.09   543.1  729.45   559.4  734.23   579.6  742.02   612.5  751.08
#Mann= 6 ,-1,0
       0      .1       0   148.7    .045       0   174.2      .1       0
  191.27     .05       0  481.27     .06       0  588.77      .1       0
Bank Sta=148.7,174.2
XS Rating Curve= 0 ,0
Exp/Cntr(USF)=0,0
Exp/Cntr=0.3,0.1

Type RM Length L Ch R = 1 ,2596    ,59.7,61.9,60.5
BEGIN DESCRIPTION:
Structure 2 XS 3
END DESCRIPTION:
XS GIS Cut Line= 6
1624184.76419584392700.9073669451623874.23978116392648.864168954
1623673.00608226392678.3553144821623300.02982999392740.807152071
1623265.33436466392733.8680590061623189.00434094392877.854240115
#Sta/Elev= 30
       0   782.5    49.3  767.49   106.1  753.54   223.7  733.69     310  716.06
   362.3   709.8   369.6  707.48   373.6  704.52   381.7   701.2   393.8  699.66
   401.9  701.33   426.2  707.65   438.3  708.43   478.7  707.56   551.9  703.97
   722.3  701.18   758.7   702.2   783.2  700.97   892.3   700.9   916.4   699.5
   931.7  701.67   939.4  705.57     953  705.95     962   710.5   975.6  714.87
   984.7  720.09   998.2  718.53  1057.1  718.81  1079.7  723.47  1094.8  725.17
#Mann= 10 ,-1,0
       0      .1       0     140     .05       0     240     .06       0
  344.86     .07       0   381.7    .045       0   401.9     .07       0
  444.86     .06       0  813.79     .05       0  843.79     .06       0
 1041.84     .05       0
#XS Ineff= 2 , 0
                          509.57          746.38
Permanent Ineff=
       F       F
Bank Sta=381.7,401.9
XS Rating Curve= 0 ,0
Exp/Cntr(USF)=0,0
Exp/Cntr=0.3,0.1

Type RM Length L Ch R = 1 ,2534    ,709.9,698.8,689.1
BEGIN DESCRIPTION:
Structure 2 XS 2
END DESCRIPTION:
XS GIS Cut Line= 6
 1624233.3378473392671.4162214161623860.36159503392596.820970962
1623350.33825472392692.2335006131623296.56028346392699.172593678
1623241.04753893392690.4987273461623140.43068949 392865.71082725
#Sta/Elev= 30
       0  793.81    70.6  770.63   123.6  755.89   180.7  741.73   241.4  730.82
   292.4  716.39   445.4  708.22   457.6   706.3   469.7  700.52   481.9  699.54
   491.9   700.5   514.3  707.06   526.4  708.39   542.6  706.67   587.4  705.59
   647.7  705.94   717.5  702.35   868.9  700.88   913.7  696.27   953.6  697.34
   991.3  695.24  1009.8  695.86  1016.8  698.56  1047.1  701.19  1075.9  718.16
  1114.5  728.99  1122.9  728.83  1159.8  733.81  1196.7  726.93  1211.8  727.18
#Mann= 10 ,-1,0
       0      .1       0     190     .05       0     210     .06       0
     300     .05       0   469.7    .045       0   491.9      .1       0
  595.49     .06       0  898.29     .05       0  993.61     .06       0
  1169.8     .05       0
#XS Ineff= 2 , 0
                          654.21          728.83
Permanent Ineff=
       F       F
Bank Sta=469.7,491.9
XS Rating Curve= 0 ,0
Exp/Cntr(USF)=0,0
Exp/Cntr=0.3,0.1

Type RM Length L Ch R = 1 ,1835    ,339.5,337.9,337.5
BEGIN DESCRIPTION:
Structure 2 XS 1
END DESCRIPTION:
XS GIS Cut Line= 2
1623480.44624969 392239.457678091623058.89634597392836.219681722
#Sta/Elev= 30
       0  770.16    35.6   766.1    50.3  763.73    69.9  759.12    84.2  754.37
    94.4   751.8    99.3     749   127.3  723.21   138.8  718.76   153.1  709.81
     158  708.05   167.8  705.98   196.2  702.35   241.3  700.13   477.4  697.88
   481.3  697.58   503.3  691.71   510.6  690.88   517.6  691.73   526.2  697.17
   546.3  697.88   560.7  701.85   592.2  716.81   608.6  722.42   623.3  724.86
   643.9  729.95   652.3   732.7     664  733.58   691.8  737.56   730.6   740.3
#Mann= 6 ,-1,0
       0      .1       0     220     .05       0     480     .06       0
   503.3    .045       0   517.6     .06       0     600     .05       0
Bank Sta=503.3,517.6
XS Rating Curve= 0 ,0
Exp/Cntr(USF)=0,0
Exp/Cntr=0.3,0.1

Type RM Length L Ch R = 1 ,1497    ,496.2,497.5,498.5
XS GIS Cut Line= 6
1623322.90313322392071.2318475751623147.61445432392122.150777604
1622992.68596926392328.9272544241622903.75176392392480.188434839
1622809.83594126392618.6602707511622758.80159451392701.395013422
#Sta/Elev= 30
       0  750.67    65.4  741.66    93.7  735.91   123.7  725.55   140.4  714.37
     157  706.29   173.7  701.08   180.8  700.06   203.9  698.32     401  698.67
   426.8  697.24   532.7  694.83   543.8  693.78   552.5  688.71   555.7   687.7
   564.1  687.45   573.6688.7911   583.9  690.97   607.7  694.04   655.8  693.49
   665.5  694.21   679.7  699.81   709.1  717.49   722.9  719.72   779.6  720.08
   795.4  721.67   800.1  723.04   809.9  727.79   851.8   738.4     881  749.84
#Mann= 7 ,-1,0
       0      .1       0  450.91     .07       0   552.5    .045       0
   573.6     .06       0  686.44     .07       0  803.76     .05       0
  873.76      .1       0
Bank Sta=552.5,573.6
XS Rating Curve= 0 ,0
Exp/Cntr(USF)=0,0
Exp/Cntr=0.3,0.1

Type RM Length L Ch R = 1 ,1000    ,200.4,202.1,203.9
BEGIN DESCRIPTION:
Structure 1 XS 4
END DESCRIPTION:
XS GIS Cut Line= 6
1623076.02841859391601.892586527 1622654.0183395392016.074533671
1622487.53146775392218.9281305821622439.80584143392276.851571172
1622384.08974551392344.4009767621622321.01795597 392569.66094461
#Sta/Elev= 30
       0  721.59    33.5  717.11    55.2  711.75   120.6  702.03   242.2  694.29
   344.1  692.61   534.9  693.29     552  690.87   581.7  690.27   606.9  686.72
   788.5  688.21   793.7  687.11   798.9  683.88   806.1   682.4   814.4  682.85
  816.99683.8199   823.2  687.81   828.9  689.08   853.7  689.74   912.8  689.16
  1029.4  694.33  1049.7  694.16  1070.5  695.75  1105.3  703.35  1141.1  709.92
    1166  717.28  1199.3  720.13    1220  724.83  1228.3  724.66  1250.3  732.23
#Mann= 12 ,-1,0
       0     .05       0      20     .07       0      70     .05       0
     160     .06       0     300      .1       0     350     .06       0
     440     .07       0   798.9    .045       0  816.99     .07       0
  883.73     .06       0 1056.34     .05       0 1216.34      .1       0
#XS Ineff= 2 , 0
                          854.49          699.34
Permanent Ineff=
       F       F
Bank Sta=798.9,816.99
XS Rating Curve= 0 ,0
Exp/Cntr(USF)=0,0
Exp/Cntr=0.3,0.1

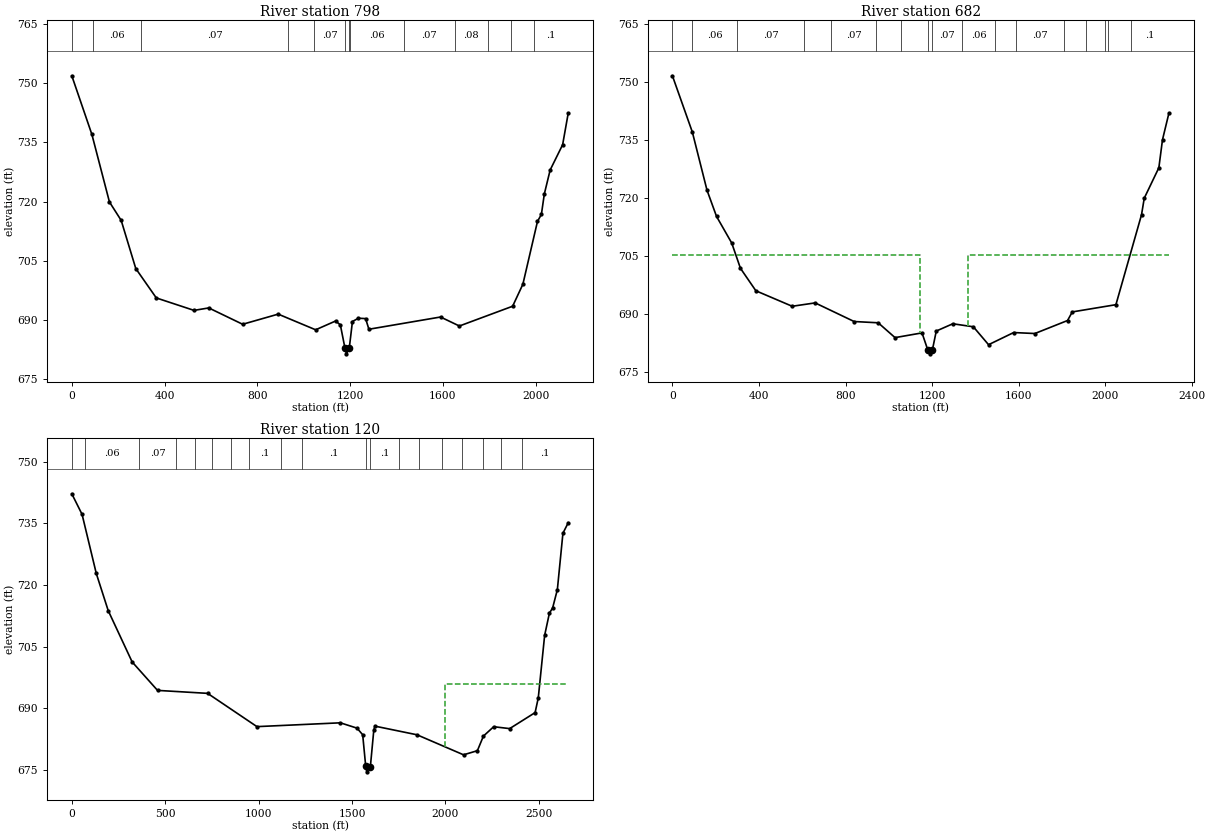
Type RM Length L Ch R = 1 ,798     ,116.5,115.8,114.3
BEGIN DESCRIPTION:
Structure 1 XS 3
END DESCRIPTION:
XS GIS Cut Line= 6
1623145.63500928391304.4148875161622625.20302937 391479.62698742
 1622474.2777552391961.8939554711622234.87904444392140.575601907
1621913.94599016 392258.540184021622047.52353167392674.885767949
#Sta/Elev= 30
       0  751.88    86.6  737.02   162.3  719.91   212.9  715.25   275.9  703.04
   364.4   695.6   526.9  692.45   590.6  693.07   736.7  688.93   889.9   691.5
  1051.4  687.53  1137.1  689.75  1157.9  688.79  1177.7   682.9  1184.4  681.44
  1196.6682.9916    1210  689.63  1235.5  690.46  1266.8  690.37    1281  687.67
  1589.9  690.77  1671.1  688.49  1900.7   693.5  1944.9  699.07  2007.9     715
  2024.7  716.75  2037.4  721.94  2062.5  728.01  2116.3  734.41  2140.6  742.47
#Mann= 13 ,-1,0
       0     .05       0      90     .06       0     300     .07       0
  930.23     .08       0 1045.68     .07       0  1177.7    .045       0
  1196.6     .07       0 1201.65     .06       0 1431.41     .07       0
 1650.96     .08       0 1793.34     .07       0 1893.34     .05       0
 1993.34      .1       0
Bank Sta=1177.7,1196.6
XS Rating Curve= 0 ,0
Exp/Cntr(USF)=0,0
Exp/Cntr=0.3,0.1

Type RM Length L Ch R = 1 ,682     ,565.3,562.2,555.3
BEGIN DESCRIPTION:
Structure 1 XS 2
END DESCRIPTION:
XS GIS Cut Line= 6
1623143.90023602391252.3716895251622550.60777892391439.727202293
1622377.13045228 391885.563931751622226.20517811392033.019659392
1621811.59436744392208.2317592951621978.13260102392704.376913477
#Sta/Elev= 30
       0  751.55    92.1  737.01   159.9  721.98     204   715.2   274.1  708.34
   314.4  701.81   385.7     696   553.5     692   659.6  692.87   839.7  688.06
   950.9  687.73  1028.8   683.9  1153.4  685.12  1179.7  680.78  1188.7  679.71
 1201.41 680.738  1219.3   685.6  1295.7  687.48  1390.6   686.7  1460.9  682.07
  1576.9  685.21  1674.9  684.96  1825.9  688.32  1847.8  690.54  2049.4  692.41
  2167.7  715.64  2180.3  719.92  2247.8  727.79  2264.7  735.05  2294.1  741.85
#Mann= 17 ,-1,0
       0     .05       0      90     .06       0     300     .07       0
     610     .06       0  732.17     .07       0   942.4     .06       0
 1057.38     .08       0  1179.7    .045       0 1201.41     .07       0
 1340.03     .06       0 1488.61     .05       0 1588.61     .07       0
 1810.72     .08       0 1910.72     .05       0 2000.72     .07       0
 2010.72     .05       0 2120.72      .1       0
#XS Ineff= 2 , 0
         1143.06  705.22 1365.92          705.22
Permanent Ineff=
       F       F
Bank Sta=1179.7,1201.41
XS Rating Curve= 0 ,0
Exp/Cntr(USF)=0,0
Exp/Cntr=0.3,0.1

Type RM Length L Ch R = 1 ,120     ,,,
BEGIN DESCRIPTION:
Structure 1 XS 1
END DESCRIPTION:
XS GIS Cut Line= 6
1623123.08295682  391202.0632648 1622071.8103574391188.185078669
1621953.84577529391561.1613309391621839.35073971391857.807559489
1621643.32136061392194.3535731651621816.79868724392671.416221416
#Sta/Elev= 30
       0   742.2      55  737.19     131  722.83     195  713.78     323  701.32
     459   694.4     727  693.68   991.1  685.59  1437.7  686.52  1526.9  685.22
  1557.1  683.62  1573.3  675.96  1579.1   674.6  1598.3675.8723  1616.6  684.75
  1622.8  685.71  1847.8  683.61    2097  678.74  2171.1  679.74  2203.4  683.29
  2258.4  685.57  2343.9  685.11  2480.1     689  2497.1   692.6  2531.1  707.77
  2556.7   713.2  2573.7  714.41  2599.2   718.9    2629   732.6  2657.6  735.18
#Mann= 19 ,-1,0
       0     .05       0      70     .06       0     360     .07       0
     560     .06       0     660      .1       0     750     .06       0
     850     .05       0     950      .1       0 1121.36     .05       0
 1231.36      .1       0  1573.3    .045       0  1598.3      .1       0
 1752.55     .05       0 1860.53     .06       0 1980.53      .1       0
 2090.53     .06       0    2200     .07       0    2300     .05       0
    2410      .1       0
#XS Ineff= 2 , 0
                         1997.12          696.07
Permanent Ineff=
       F       F
Bank Sta=1573.3,1598.3
XS Rating Curve= 0 ,0
Exp/Cntr(USF)=0,0
Exp/Cntr=0.3,0.1
LCMann Table=0

Chan Stop Cuts=-1
Use User Specified Reach Order=0
Composite Channel Slope=5